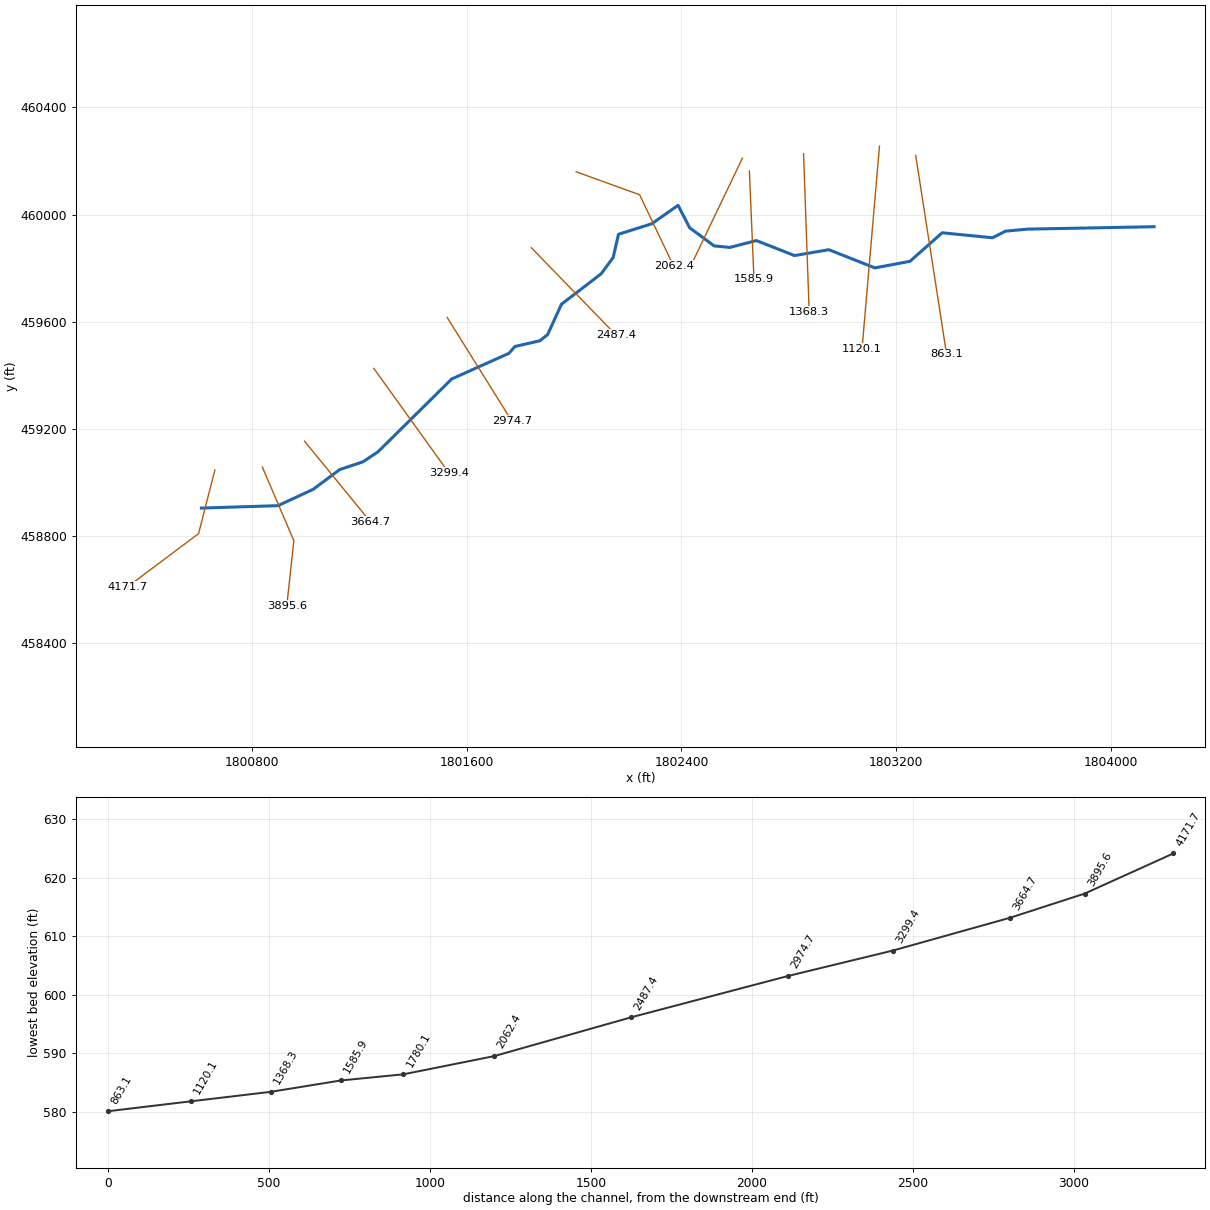
--- RUSHCREEK.prj (project) ---

Proj Title=RUSHCREEK
Current Plan=p01
Default Exp/Contr=0,0
English Units
Geom File=g01
Flow File=f01
Plan File=p01
BEGIN DESCRIPTION:
END DESCRIPTION:
DSS Export Rating Curves= 0
DSS Export Rating Curve Sorted= 0
DSS Export Volume Flow Curves= 0
DXF OffsetX= 0
DXF OffsetY= 0
DXF ScaleX= 0
DXF ScaleY= 0

--- RUSHCREEK.p01 (plan) ---

Plan Title=Floodplain
Program Version=4.00
Geom File=g01
Flow File=f01
K Sum by GR=0
Std Step Tol=0.01
Critical Tol=0.01
Num of Std Step Trials=20
Max Error Tol=0.3
Flow Tol Ratio=0.001
Split Flow NTrial=30
Split Flow Tol=0.02
Split Flow Ratio=0.02
Log Output Level=0
Friction Slope Method=1
Unsteady Friction Slope Method=2
Unsteady Bridges Friction Slope Method=1
Global Log Level=0
CheckData=False
Run HTab=0
Run UNet=0
Run PostProcess=0
UNET Theta=0
UNET Theta Warmup=0
UNET ZTol=0
UNET ZSATol=0
UNET MxIter=0
UNET MaxInSteps=0
UNET DtIC=0
UNET DtMin=0
UNET MaxCRTS=0
UNET WFStab=0
UNET SFStab=0
UNET WFX=0
UNET SFX=0
UNET DSS MLevel=0
UNET DZMax Abort=0
UNET Convert EG Bridges=0
UNET Use Existing IB Tables=0
UNET Froude Limit=0
UNET Froude Power=0
Write IC File=0
Echo Input=False
Echo Output=False
Write Detailed=0

--- RUSHCREEK.f01 (steady flow) ---

Flow Title=NFF Regression Equation
Program Version=4.10
Number of Profiles= 1
Profile Names=P100yr
River Rch & RM=RUSHCREEK,Main            ,4171.7
 1015.29
River Rch & RM=RUSHCREEK,Main            ,2062.4
1062.192
River Rch & RM=RUSHCREEK,Main            ,1780.1
1749.582
Boundary for River Rch & Prof#=RUSHCREEK,Main            , 1
Up Type= 0
Dn Type= 3
Dn Slope=0.0065
DSS Import GetInterval= 0
DSS Import GetPeak= 0
DSS Import FillOption= 0

--- RUSHCREEK.g01 (geometry) ---

Geom Title=USGS 10m DEM
Program Version=4.10

River Reach=RUSHCREEK       ,Main
Reach XY= 30
     1800610.981      458903.726     1800896.079      458912.633
     1801027.172      458973.441     1801126.051      459047.369
      1801213.11      459076.566     1801268.533      459113.361
     1801543.741      459385.791     1801756.681      459481.499
     1801779.743      459507.251     1801871.992      459528.392
     1801901.204      459551.454     1801952.709      459664.843
     1802100.705      459778.645     1802145.314      459839.066
     1802165.395       459926.25     1802289.417      459965.419
     1802387.377        460034.4      1802430.63      459950.337
     1802521.889      459882.843     1802580.375      459877.062
     1802679.167      459902.767     1802821.212       459846.71
     1802949.378      459868.558     1803120.745        459800.7
     1803251.543      459825.154     1803371.673      459931.782
     1803558.987      459913.192     1803607.432      459937.667
     1803687.184      459945.321     1804161.413      459954.437

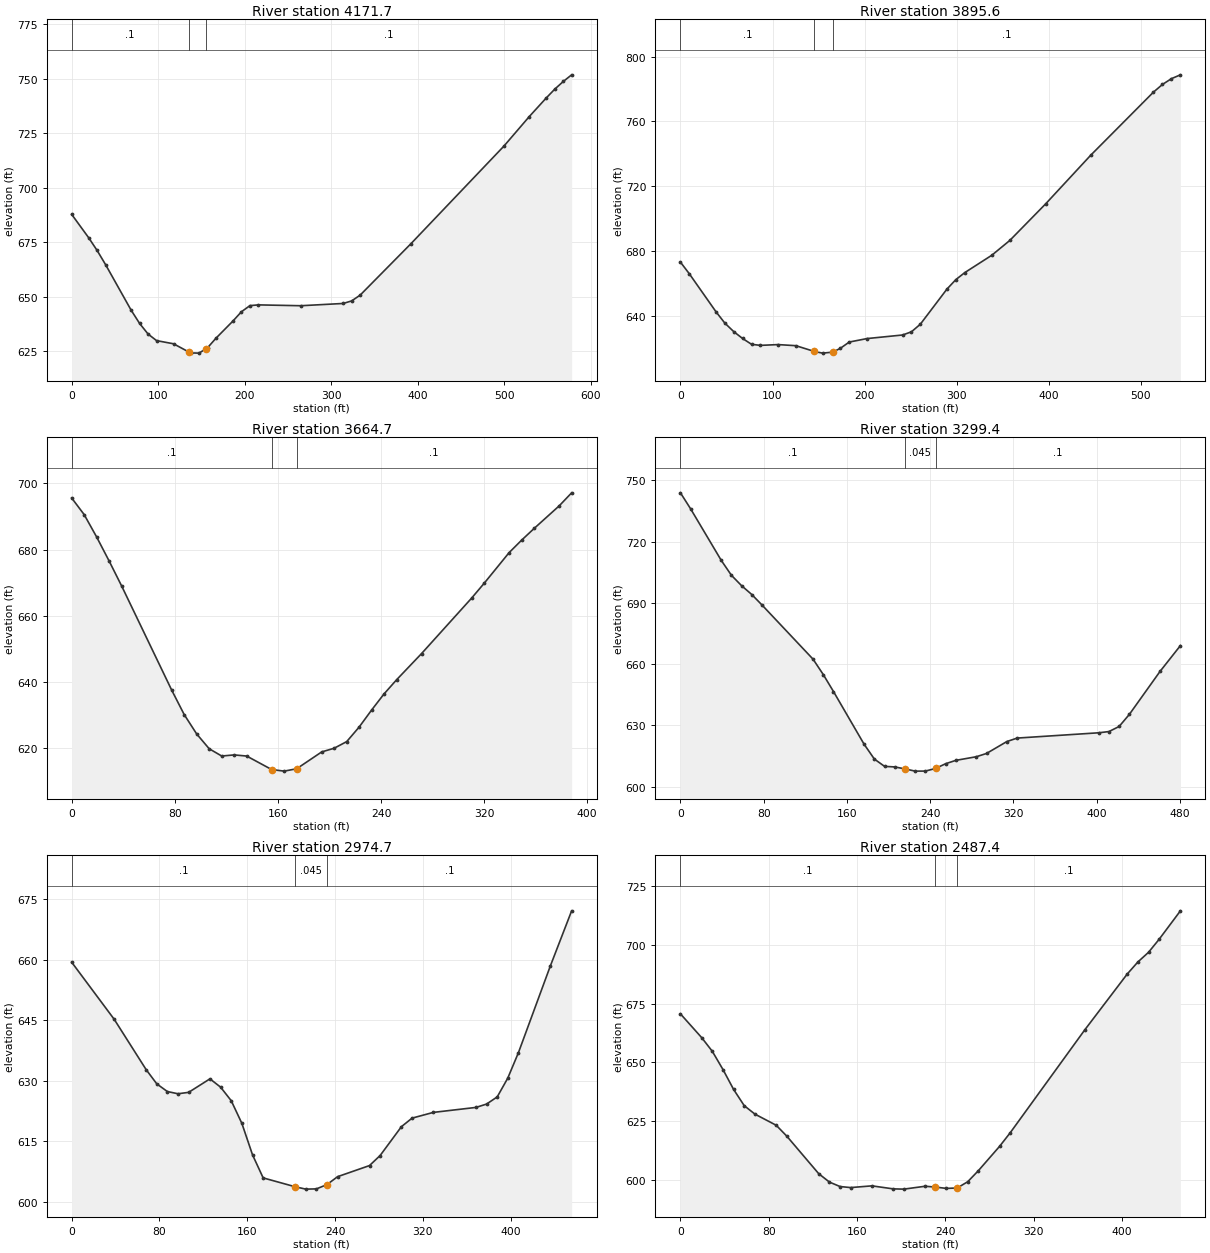
Type RM Length L Ch R = 1 ,4171.7  ,259.3,276.1,292.6
XS GIS Cut Line= 3
     1800661.135      459045.932     1800600.371      458808.301
     1800334.529      458608.649
#Sta/Elev= 30
       0  687.81    19.6  677.11    29.4  671.25    39.2  664.73    68.7  643.85
    78.5  637.75    88.3  632.88    98.1  629.87   117.7  628.42     135  624.73
   137.4  624.24   147.2  624.13     155   626.1     157   626.6   166.8     631
   186.4  638.88   196.2  643.13     206  645.93   215.8  646.27   264.8  645.88
   313.7  646.92   323.5  648.09   333.3  650.73     392  674.34   499.5  719.15
   528.8  732.71   548.4  741.24   558.2  745.27     568  748.78   577.7  751.84
#Mann= 3 , 0 , 0
       0      .1       0     135    .045       0     155      .1       0
Bank Sta=135,155
XS Rating Curve= 0 ,0
Exp/Cntr=0.3,0.1

Type RM Length L Ch R = 1 ,3895.6  ,223.8,230.8,237.8
XS GIS Cut Line= 3
     1800838.002      459056.782     1800955.483      458781.788
     1800929.147      458539.349
#Sta/Elev= 30
       0  673.34     9.6  666.19    38.6  642.75    48.2  635.77    57.9   630.5
    67.5  626.28    77.2   622.7    86.8  622.04   106.1  622.52   125.4  621.84
   145.4  618.29   154.3  617.26   165.4  617.87   173.6  620.21   183.3  624.09
   202.6  626.23   241.2  628.43   250.8  630.39   260.4  635.02   289.4  656.73
     299  662.53   308.8   666.9   338.1  677.58   357.6  686.68   396.6  709.26
   445.4  739.15   513.6  778.08   523.4  782.82   533.2   786.4   542.9  788.75
#Mann= 3 , 0 , 0
       0      .1       0   145.4    .045       0   165.4      .1       0
Bank Sta=145.4,165.4
XS Rating Curve= 0 ,0
Exp/Cntr=0.3,0.1

Type RM Length L Ch R = 1 ,3664.7  ,366.7,365.3,363.5
XS GIS Cut Line= 2
     1800995.337      459153.353     1801240.562      458852.789
#Sta/Elev= 30
       0  695.58     9.7  690.56    19.4  683.79    29.1  676.53    38.8     669
    77.6   637.6    87.3  630.22      97  624.36   106.7   619.9   116.4  617.71
   126.1  618.04   135.8   617.7   155.2  613.62   164.9  613.15   174.6  613.87
     194  618.95   203.6  620.05   213.4  622.06     223  626.43   232.8  631.63
   242.4  636.47   252.1  640.72   271.5  648.64   310.3  665.36     320  669.82
   339.4  679.09   349.1  682.85   358.8  686.38   378.2  693.18   387.9  697.13
#Mann= 3 , 0 , 0
       0      .1       0   155.2    .045       0   174.6      .1       0
Bank Sta=155.2,174.6
XS Rating Curve= 0 ,0
Exp/Cntr=0.3,0.1

Type RM Length L Ch R = 1 ,3299.4  ,326.2,324.7,323
XS GIS Cut Line= 2
     1801253.523      459425.266     1801533.471      459034.641
#Sta/Elev= 30
       0  743.85     9.8     736    39.2  710.79      49  703.46    58.8  698.35
    68.6  694.03    78.5  688.85   127.5  662.35   137.3  654.83   147.1  646.53
   176.5  620.74   186.4  613.45   196.2  609.86     206  609.59   215.8  608.63
   225.6  607.53   235.4  607.55   245.2  608.83     255  611.18   264.8  612.81
   284.4  614.58   294.2  616.18   313.8  622.03   323.7  623.72   402.1  626.31
   411.9  626.91   421.7  629.41   431.5  635.31     461  656.37   480.6  669.02
#Mann= 3 , 0 , 0
       0      .1       0   215.8    .045       0   245.2      .1       0
Bank Sta=215.8,245.2
XS Rating Curve= 0 ,0
Exp/Cntr=0.3,0.1

Type RM Length L Ch R = 1 ,2974.7  ,481.6,487.3,491.3
XS GIS Cut Line= 2
     1801526.961       459615.37     1801767.846      459228.651
#Sta/Elev= 30
       0  659.36    38.8  645.21    67.9  632.76    77.6  629.24    87.2  627.35
    96.9   626.8   106.6  627.15     126  630.49   135.7  628.44   145.4  625.08
   155.1  619.47   164.8  611.69   174.5  605.98   203.6  603.79   213.3   603.2
     223  603.26   232.6  604.31   242.3  606.28   271.4  609.03   281.1  611.52
   300.5  618.66   310.2  620.77   329.6  622.19   368.4  623.42   378.1  624.25
   387.8  626.03   397.4  630.67   407.1  636.96   436.2  658.43   455.6  672.07
#Mann= 3 , 0 , 0
       0      .1       0   203.6    .045       0   232.6      .1       0
Bank Sta=203.6,232.6
XS Rating Curve= 0 ,0
Exp/Cntr=0.3,0.1

Type RM Length L Ch R = 1 ,2487.4  ,432.7,424.9,416.6
XS GIS Cut Line= 2
     1801840.763      459875.787     1802155.867      459550.266
#Sta/Elev= 30
       0  670.61    19.3  660.48    28.9  654.68    38.6   646.9    48.2  638.48
    57.8   631.6    67.5  628.01    86.8  623.27    96.4  618.63   125.3  602.69
     135  599.13   144.6  597.24   154.2   596.8   173.5  597.53   192.8  596.25
   202.4  596.14   221.7  597.36   230.8  597.02     241  596.45   250.8  596.63
   260.3  599.29   269.9  603.96   289.2  614.34   298.8   620.1   366.3  663.78
   404.8  687.53   414.5  692.68   424.1  696.76   433.8  702.35     453  714.39
#Mann= 3 , 0 , 0
       0      .1       0   230.8    .045       0   250.8      .1       0
Bank Sta=230.8,250.8
XS Rating Curve= 0 ,0
Exp/Cntr=0.3,0.1

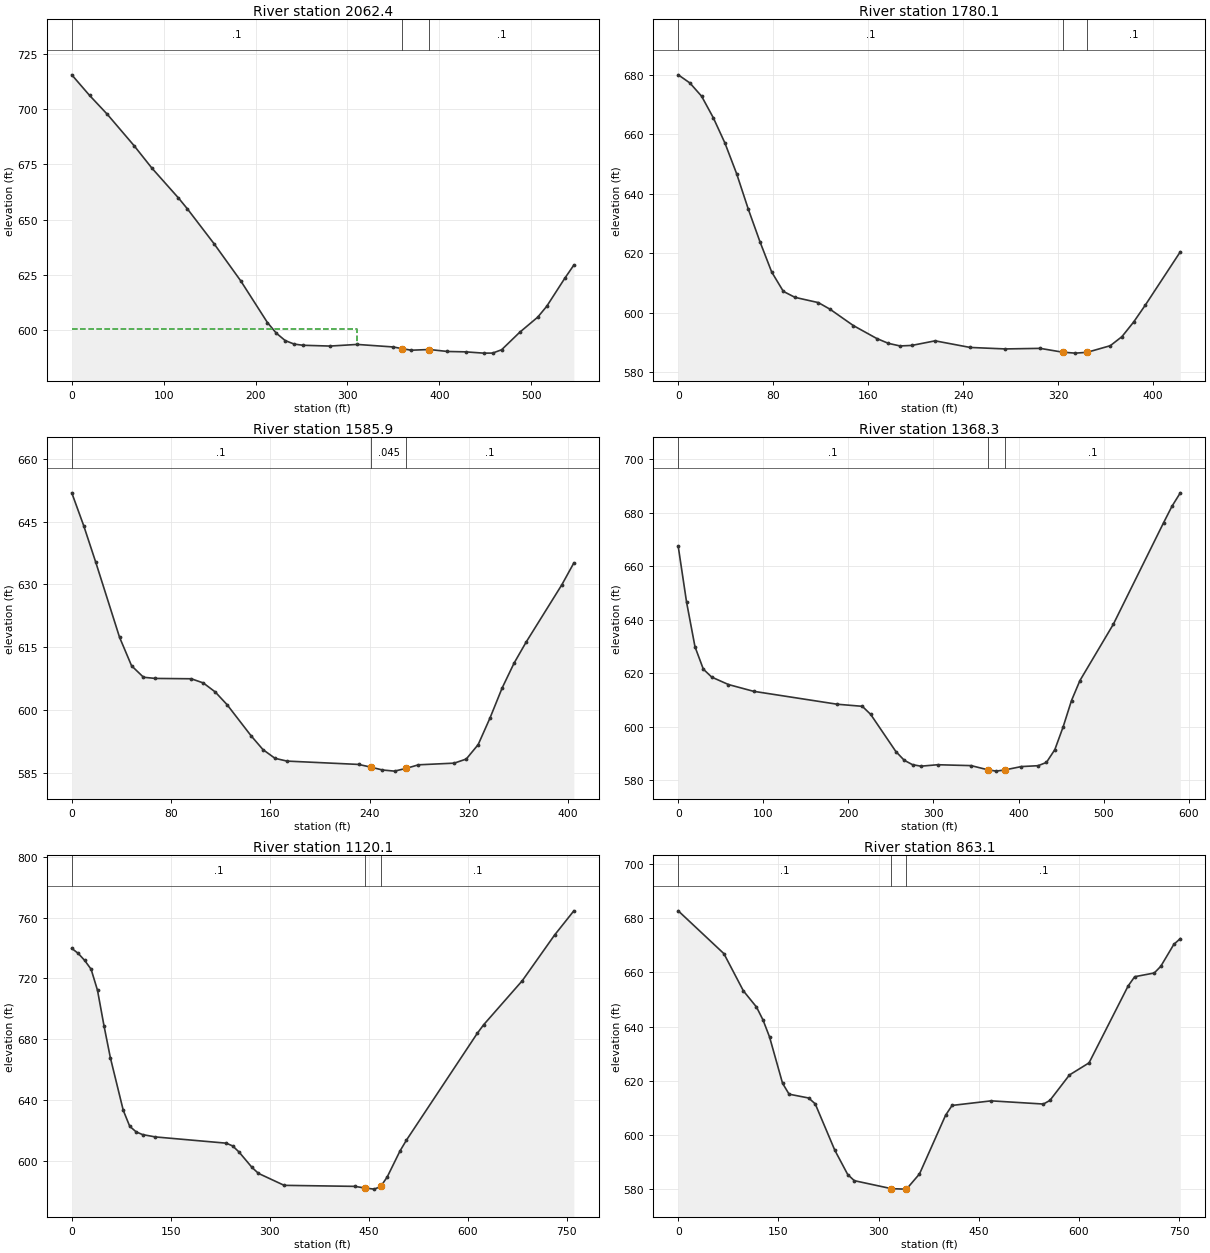
Type RM Length L Ch R = 1 ,2062.4  ,307,282.3,240.2
XS GIS Cut Line= 3
      1802007.43      460159.641     1802243.993      460073.855
     1802370.665      459807.701
#Sta/Elev= 30
       0  715.57    19.4  706.23    38.7  697.68    67.8  683.49    87.1  673.37
   116.1   659.8   125.8  654.88   154.8   639.1   183.9  622.24   212.9  603.39
   222.6  598.56   232.3   595.2     242  593.62   251.6  593.08   281.1  592.72
   310.6  593.46   349.9  592.31   359.7  591.53   369.5  590.84   389.2  591.16
   408.8  590.27   428.5   590.1   448.1  589.52     458  589.54   467.8  591.05
   487.4  598.93   507.1  605.82   516.9  610.74   536.6  623.46   546.4   629.4
#Mann= 3 , 0 , 0
       0      .1       0   359.7    .045       0   389.2      .1       0
#XS Ineff= 2 , 0
           310.2  600.53
Permanent Ineff=
       F       F
Bank Sta=359.7,389.2
XS Rating Curve= 0 ,0
Exp/Cntr=0.3,0.1

Type RM Length L Ch R = 1 ,1780.1  ,181.6,194.2,206
XS GIS Cut Line= 2
     1802627.221      460210.422     1802444.676       459829.05
#Sta/Elev= 30
       0  679.91     9.8  677.18    19.7  672.71    29.5  665.51    39.3  657.01
    49.2  646.67      59  634.78    68.8  623.86    78.7  613.66    88.5  607.16
    98.3  605.15     118  603.38   127.8  601.17   147.5  595.66   167.2  591.32
     177  589.69   186.8  588.82   196.7     589   216.3  590.54   245.8  588.32
   275.3  587.82   304.8  588.01   323.8  586.72   334.3  586.41   344.2  586.67
   363.8   588.9   373.6  591.93   383.5  596.86   393.3  602.53   422.8  620.46
#Mann= 3 , 0 , 0
       0      .1       0   323.8    .045       0   344.2      .1       0
Bank Sta=323.8,344.2
XS Rating Curve= 0 ,0
Exp/Cntr=0.3,0.1

Type RM Length L Ch R = 1 ,1585.9  ,217.7,217.6,217.6
XS GIS Cut Line= 2
     1802653.187      460162.811     1802670.267      459758.598
#Sta/Elev= 30
       0  651.89     9.6  644.05    19.3  635.32    38.5  617.36    48.2  610.54
    57.8   607.8    67.4  607.52    96.3  607.44     106  606.44   115.6  604.29
   125.2  601.23   144.5  593.81   154.1   590.5   163.8  588.42   173.4  587.76
   231.2  586.96   240.8  586.33   250.4  585.63   260.1  585.36   269.7  586.04
   279.4  586.87   308.2  587.27   317.9  588.25   327.5   591.7   337.1  598.11
   346.8  605.23   356.4  611.16     366  616.13   394.9   629.9   404.6  635.13
#Mann= 3 , 0 , 0
       0      .1       0   240.8    .045       0   269.7      .1       0
Bank Sta=240.8,269.7
XS Rating Curve= 0 ,0
Exp/Cntr=0.3,0.1

Type RM Length L Ch R = 1 ,1368.3  ,250.9,248.3,244.7
XS GIS Cut Line= 2
     1802855.086      460227.349     1802875.919      459637.506
#Sta/Elev= 30
       0  667.45     9.8  646.61    19.7  629.93    29.5  621.56    39.4  618.58
      59  615.81    88.5  613.28   186.9  608.44   216.4  607.66   226.2  604.65
   255.8  590.76   265.6   587.5   275.4  585.83   285.3  585.27   304.9  585.81
   344.3  585.48   363.9  583.92   373.8  583.42   383.9  583.87   403.3  585.12
     423  585.45   432.8  586.67   442.7  591.46   452.5  600.01   462.3  609.83
   472.2   617.3   511.5  638.38   570.5  676.31   580.4  682.49   590.2  687.51
#Mann= 3 , 0 , 0
       0      .1       0   363.9    .045       0   383.9      .1       0
Bank Sta=363.9,383.9
XS Rating Curve= 0 ,0
Exp/Cntr=0.3,0.1

Type RM Length L Ch R = 1 ,1120.1  ,253.7,257,257
XS GIS Cut Line= 2
      1803138.02      460255.562      1803072.97      459497.485
#Sta/Elev= 30
       0  739.77     9.8  736.45    19.5  731.87    29.3  726.07      39  712.24
    48.8  689.08    58.5     668      78  633.55    87.8  623.06    97.6  619.35
   107.3  617.58   126.8  616.04   234.1  611.95   243.9  610.13   253.6  606.09
   273.1  596.06   282.9  592.13   321.9  584.28   429.2  583.61   444.3  582.51
   458.5   581.8   468.2  583.53     478  589.73   497.5  606.88   507.2  613.94
   614.5     684   624.3   689.7   682.8  718.57   731.6  748.44   760.9  764.39
#Mann= 3 , 0 , 0
       0      .1       0   444.3    .045       0   468.2      .1       0
Bank Sta=444.3,468.2
XS Rating Curve= 0 ,0
Exp/Cntr=0.3,0.1

Type RM Length L Ch R = 1 ,863.1   ,863.6,863.1,864.4
XS GIS Cut Line= 2
     1803273.123      460220.536      1803388.21       459477.47
#Sta/Elev= 30
       0  682.72    68.4  666.93    97.6   653.2   117.2  647.25     127  642.46
   136.7  636.24   156.2  619.16     166  615.12   195.3  613.71   205.1  611.57
   234.4   594.5   253.9  585.46   263.7  583.23   319.3  580.28   339.3  580.11
   341.8  580.11   361.3  585.71   400.4  607.36   410.1  610.97   468.7  612.66
   546.9  611.48   556.6  612.82   585.9  622.21   615.2  626.66   673.8  655.04
   683.6  658.43   712.9   659.8   722.6  662.25   742.2  670.36   751.9  672.48
#Mann= 3 , 0 , 0
       0      .1       0   319.3    .045       0   341.8      .1       0
Bank Sta=319.3,341.8
XS Rating Curve= 0 ,0
Exp/Cntr=0.3,0.1

Chan Stop Cuts=-1
Use User Specified Reach Order=0
Composite Channel Slope=5